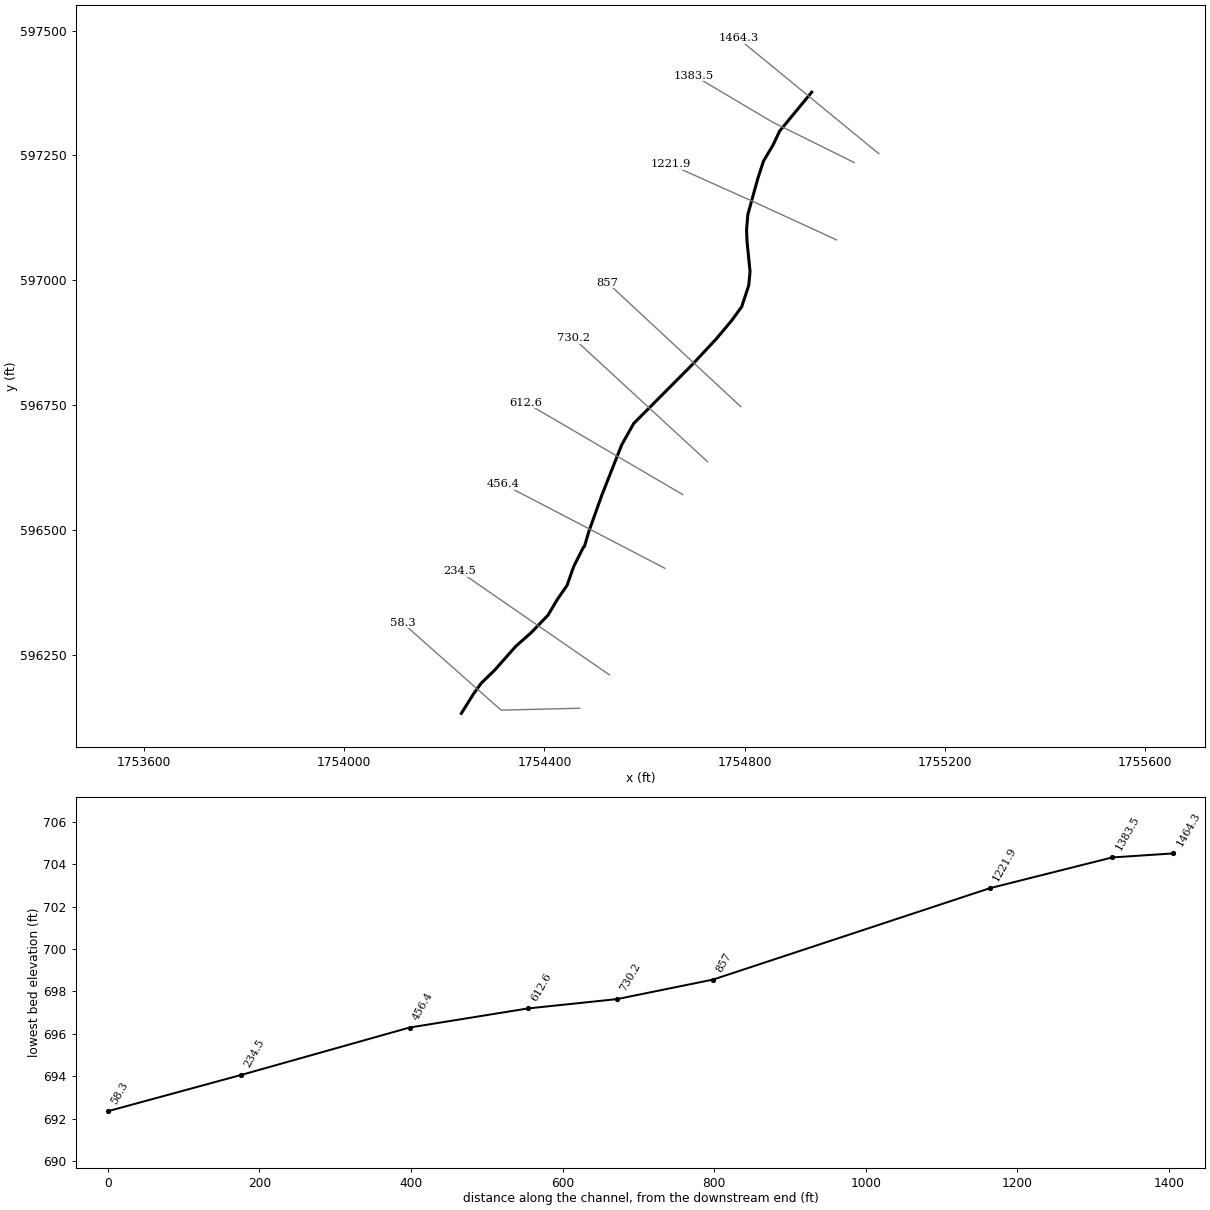
--- LFkClenden.prj (project) ---

Proj Title=LFkClenden
Current Plan=p01
Default Exp/Contr=0,0
English Units
Geom File=g01
Flow File=f01
Plan File=p01
BEGIN DESCRIPTION:
AMEC Environment & Infrastructure, 2013
Projection: NAD 1983 State Plane West Virginia South FIPS 4702 (US Feet)
Vertical Datum: NAVD 1988
END DESCRIPTION:
DSS Export Rating Curves= 0
DSS Export Rating Curve Sorted= 0
DSS Export Volume Flow Curves= 0
DXF Filename=C:\Program Files (x86)\HEC\HEC-RAS\4.1.0\LFkClenden.
DXF OffsetX= 0
DXF OffsetY= 0
DXF ScaleX= 0
DXF ScaleY= 0

--- LFkClenden.p01 (plan) ---

Plan Title=Floodplain
Program Version=4.00
Geom File=g01
Flow File=f01
K Sum by GR=0
Std Step Tol=0.01
Critical Tol=0.01
Num of Std Step Trials=20
Max Error Tol=0.3
Flow Tol Ratio=0.001
Split Flow NTrial=30
Split Flow Tol=0.02
Split Flow Ratio=0.02
Log Output Level=0
Friction Slope Method=1
Unsteady Friction Slope Method=2
Unsteady Bridges Friction Slope Method=1
Global Log Level=0
CheckData=False
Run HTab=0
Run UNet=0
Run PostProcess=0
UNET Theta=0
UNET Theta Warmup=0
UNET ZTol=0
UNET ZSATol=0
UNET MxIter=0
UNET MaxInSteps=0
UNET DtIC=0
UNET DtMin=0
UNET MaxCRTS=0
UNET WFStab=0
UNET SFStab=0
UNET WFX=0
UNET SFX=0
UNET DSS MLevel=0
UNET DZMax Abort=0
UNET Convert EG Bridges=0
UNET Use Existing IB Tables=0
UNET Froude Limit=0
UNET Froude Power=0
Write IC File=0
Echo Input=False
Echo Output=False
Write Detailed=0

--- LFkClenden.f01 (steady flow) ---

Flow Title=USGS Regress. Eqn. (2010) - Western-Plateaus
Program Version=4.10
Number of Profiles= 1
Profile Names=P100yr
River Rch & RM=LFkClenden,Main            ,1464.3
     929
River Rch & RM=LFkClenden,Main            ,857
     941
River Rch & RM=LFkClenden,Main            ,456.4
     975
River Rch & RM=LFkClenden,Main            ,58.3
    1115
Boundary for River Rch & Prof#=LFkClenden,Main            , 1
Up Type= 0
Dn Type= 3
Dn Slope=0.008316
DSS Import GetInterval= 0
DSS Import GetPeak= 0
DSS Import FillOption= 0

--- LFkClenden.g01 (geometry) ---

Geom Title=USGS 3m DEM
Program Version=4.10

River Reach=LFkClenden      ,Main
Reach XY= 30
     1754934.312      597376.756     1754870.076      597298.631
     1754857.055      597270.853     1754837.958      597238.735
     1754826.673      597204.013     1754806.708      597131.964
     1754804.104      597101.582     1754804.927      597078.932
     1754811.048      597017.207     1754808.444      596989.603
     1754794.382      596946.894     1754773.548      596918.249
      1754743.34      596882.311     1754695.423      596830.749
      1754578.42      596712.943     1754554.462      596670.234
     1754514.879      596569.713     1754488.837      596496.797
     1754479.816      596466.191     1754477.679      596464.671
     1754458.325      596425.963      1754445.13      596388.463
      1754426.38       596361.38     1754406.936      596328.741
     1754373.603      596294.019     1754342.353      596266.241
     1754300.686      596219.019     1754273.603       596192.63
      1754257.63      596170.408     1754233.904      596132.213

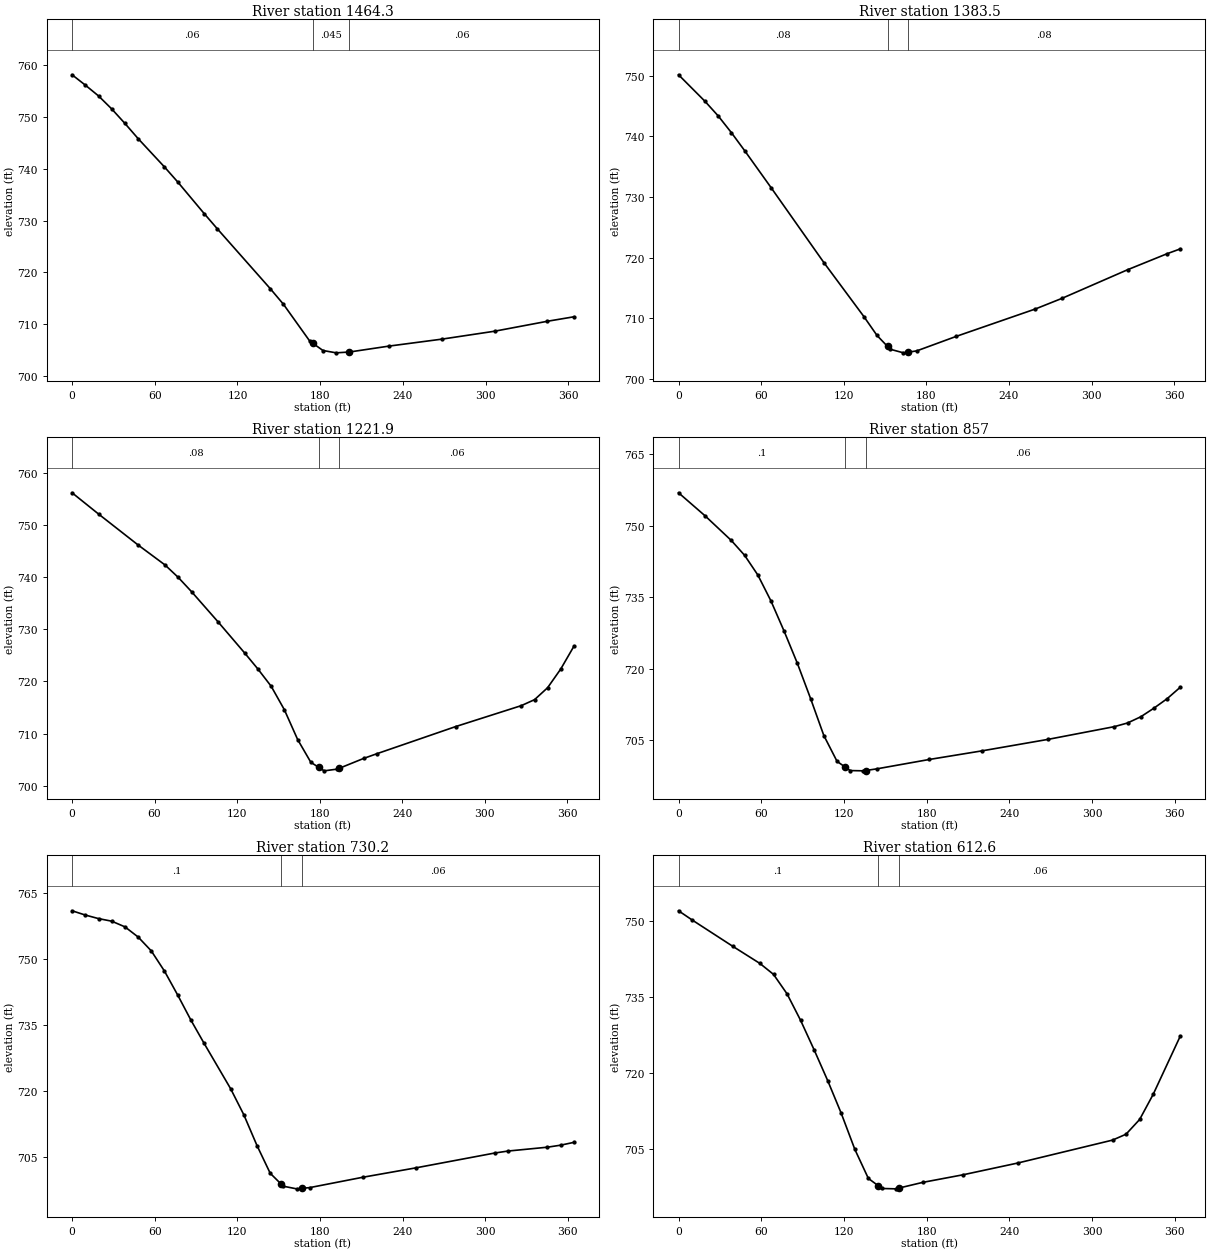
Type RM Length L Ch R = 1 ,1464.3  ,75.6,80.8,86.1
XS GIS Cut Line= 3
     1755068.543      597253.442     1754927.961      597369.031
      1754787.38      597484.621
#Sta/Elev= 22
       0  758.13     9.6  756.14    19.2  754.05    28.7  751.56    38.3  748.76
    47.9  745.82      67  740.36    76.6  737.47    95.8  731.37   105.4  728.41
   143.7   716.9   153.3  713.88   172.4  706.77   174.5  706.37     182  704.95
   191.6   704.5   201.2  704.66   229.9   705.8   268.2  707.14   306.5  708.67
   344.8  710.59     364  711.45
#Mann= 3 , 0 , 0
       0     .06       0   174.5    .045       0   201.2     .06       0
Bank Sta=174.5,201.2
XS Rating Curve= 0 ,0
Exp/Cntr=0.3,0.1

Type RM Length L Ch R = 1 ,1383.5  ,160.9,161.6,162.3
XS GIS Cut Line= 3
       1755019.3      597235.825     1754855.673      597316.967
     1754699.334      597409.924
#Sta/Elev= 20
       0  750.15    19.2  745.78    28.8  743.37    38.4  740.61    48.1  737.62
    67.3  731.52   105.7  719.15   134.6   710.3   144.2  707.17   151.8  705.37
   153.8   704.9   163.4  704.31   166.8  704.42     173  704.63   201.8  707.03
   259.2  711.54   278.4  713.28   326.2  718.01     355  720.66   364.5  721.45
#Mann= 3 , 0 , 0
       0     .08       0   151.8    .045       0   166.8     .08       0
Bank Sta=151.8,166.8
XS Rating Curve= 0 ,0
Exp/Cntr=0.3,0.1

Type RM Length L Ch R = 1 ,1221.9  ,371.2,364.9,356.5
XS GIS Cut Line= 3
     1754984.166      597080.784     1754817.611      597157.478
     1754651.858      597231.883
#Sta/Elev= 25
       0  756.15    19.3  752.07    48.2  746.11    67.6  742.32    77.2  739.94
    86.9   737.2   106.2  731.41   125.5  725.46   135.1   722.4   144.8  719.08
   154.4  714.58   164.1  708.85   173.7  704.49   179.4  703.53   183.4  702.86
   192.9  703.19   194.4  703.35     212  705.23   221.6  706.13     279  711.34
   326.8  715.36   336.4   716.5   345.9  718.79   355.5  722.39     365  726.72
#Mann= 3 , 0 , 0
       0     .08       0   179.4    .045       0   194.4     .06       0
Bank Sta=179.4,194.4
XS Rating Curve= 0 ,0
Exp/Cntr=0.3,0.1

Type RM Length L Ch R = 1 ,857     ,126.6,126.8,126.8
XS GIS Cut Line= 3
      1754792.46      596746.699     1754659.307      596870.773
     1754526.155      596994.847
#Sta/Elev= 25
       0   756.9    19.2  752.08    38.3  746.89    47.9  743.79    57.5  739.66
      67  734.23    76.6  727.86    86.2  721.12    95.8  713.72   105.4  705.97
     115  700.54   120.8  699.37   124.5  698.62   134.1  698.56   135.8  698.63
   143.7  698.97     182  700.95   220.3  702.76   268.2  705.17   316.1  707.83
   325.7   708.6   335.3   709.9   344.8   711.7   354.4  713.69     364  716.11
#Mann= 3 , 0 , 0
       0      .1       0   120.8    .045       0   135.8     .06       0
Bank Sta=120.8,135.8
XS Rating Curve= 0 ,0
Exp/Cntr=0.3,0.1

Type RM Length L Ch R = 1 ,730.2   ,112.6,117.6,122.3
XS GIS Cut Line= 2
     1754725.943      596636.573     1754458.121      596883.724
#Sta/Elev= 27
       0  760.94     9.6  759.97    19.2  759.16    28.8  758.57    38.4  757.28
      48  754.96    57.5  751.82    67.1  747.21    76.7  741.76    86.3  736.05
    95.9  730.75   115.1  720.46   124.7  714.52   134.3  707.49   143.9  701.18
     152  698.67   153.4  698.24     163  697.64     167  697.76   172.6  697.92
     211  700.27   249.4   702.4   306.9  705.79   316.5  706.24   345.2  707.12
   354.8  707.58   364.4  708.22
#Mann= 3 , 0 , 0
       0      .1       0     152    .045       0     167     .06       0
Bank Sta=152,167
XS Rating Curve= 0 ,0
Exp/Cntr=0.3,0.1

Type RM Length L Ch R = 1 ,612.6   ,155,156.2,157.2
XS GIS Cut Line= 2
     1754676.517      596570.569      1754362.57      596754.779
#Sta/Elev= 24
       0  751.98     9.8  750.18    39.4  744.97      59  741.61    68.9  739.45
    78.7  735.62    88.5  730.42    98.4  724.56   108.2  718.52     118   712.1
   127.9  704.97   137.7  699.25   144.7  697.85   147.6  697.27   157.4   697.2
   159.7  697.34   177.1  698.47   206.6  699.98     246  702.28   314.8   706.8
   324.6  707.96   334.5  710.87   344.3  715.81     364  727.31
#Mann= 3 , 0 , 0
       0      .1       0   144.7    .045       0   159.7     .06       0
Bank Sta=144.7,159.7
XS Rating Curve= 0 ,0
Exp/Cntr=0.3,0.1

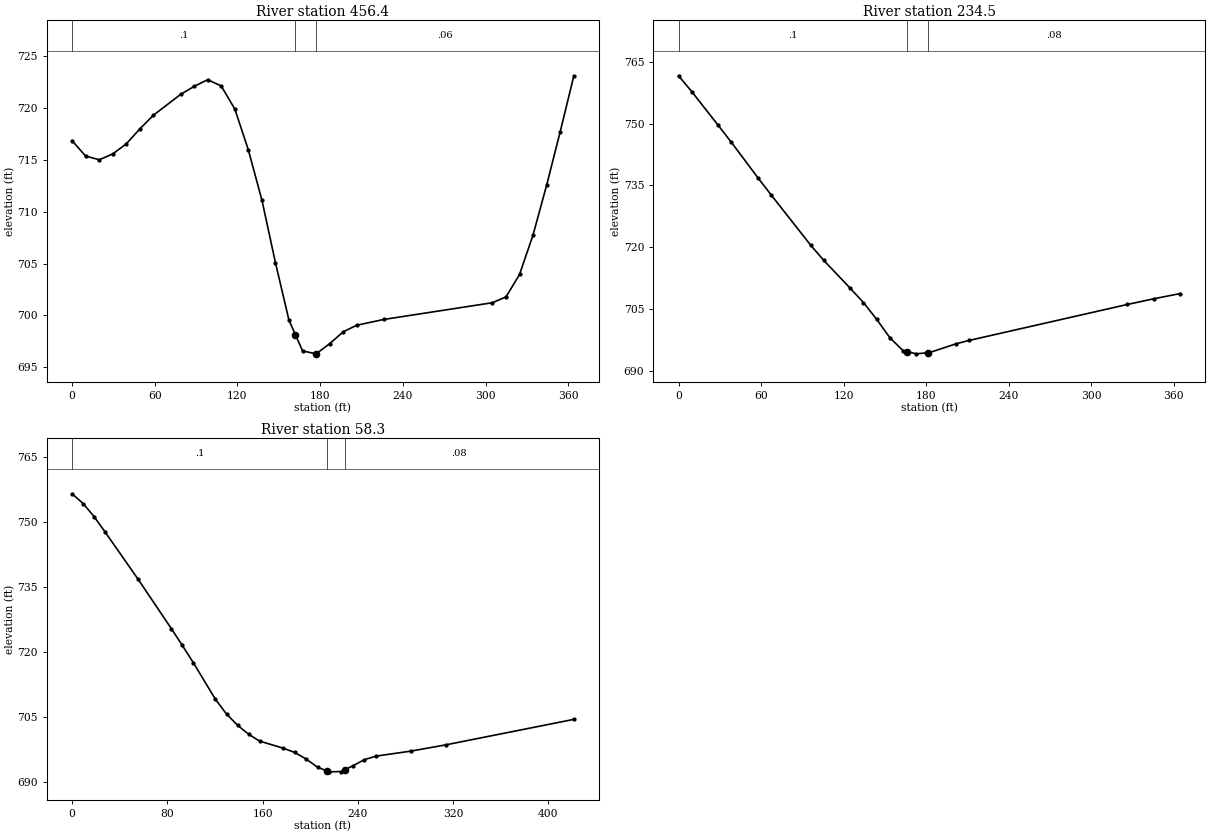
Type RM Length L Ch R = 1 ,456.4   ,224.3,221.9,218.7
XS GIS Cut Line= 2
     1754640.792      596422.833     1754318.072      596591.322
#Sta/Elev= 30
       0  716.86     9.8  715.38    19.7  715.02    29.5  715.58    39.4  716.56
    49.2     718      59  719.31    78.7  721.32    88.6   722.1    98.4  722.74
   108.2  722.14   118.1  719.91   127.9  715.97   137.8   711.1   147.6  705.07
   157.4  699.54   162.1  698.13   167.3  696.58   177.1   696.3     187  697.29
   196.8  698.43   206.6  699.06   226.3  699.62     305  701.23   314.9   701.8
   324.7  703.96   334.5  707.77   344.4   712.6   354.2  717.73   364.1  723.12
#Mann= 3 , 0 , 0
       0      .1       0   162.1    .045       0   177.1     .06       0
Bank Sta=162.1,177.1
XS Rating Curve= 0 ,0
Exp/Cntr=0.3,0.1

Type RM Length L Ch R = 1 ,234.5   ,178.7,176.2,173.1
XS GIS Cut Line= 2
     1754529.973      596209.351     1754229.972      596416.789
#Sta/Elev= 22
       0  761.66     9.6  757.82    28.8  749.63    38.4  745.49    57.6  736.91
    67.2  732.75      96   720.5   105.6  716.77   124.8  710.01   134.4  706.54
     144  702.46   153.6  697.98   163.2  694.85   166.2  694.61   172.8  694.07
   181.2  694.34   182.4  694.38   201.6   696.5   211.2  697.33   326.3  706.08
   345.5  707.46   364.7  708.73
#Mann= 3 , 0 , 0
       0      .1       0   166.2    .045       0   181.2     .08       0
Bank Sta=166.2,181.2
XS Rating Curve= 0 ,0
Exp/Cntr=0.3,0.1

Type RM Length L Ch R = 1 ,58.3    ,54.9,58.3,61.5
XS GIS Cut Line= 3
      1754470.84      596142.528     1754313.395       596138.69
     1754115.979      596313.847
#Sta/Elev= 27
       0  756.43     9.3  754.18    18.5  751.17    27.8   747.6    55.6  736.68
    83.4  725.35    92.6  721.49   101.9  717.48   120.4  709.07   129.7  705.69
     139  703.09   148.2  701.04   157.5  699.44     177  697.84   186.8  696.85
   196.6   695.3   206.4  693.39   214.1  692.57   216.1  692.36   225.9  692.43
   229.1  692.85   235.7  693.73   245.5  695.17   255.2  695.98   284.6  697.14
   313.9  698.58   421.4  704.45
#Mann= 3 , 0 , 0
       0      .1       0   214.1    .045       0   229.1     .08       0
Bank Sta=214.1,229.1
XS Rating Curve= 0 ,0
Exp/Cntr=0.3,0.1

Chan Stop Cuts=-1
Use User Specified Reach Order=0
Composite Channel Slope=5